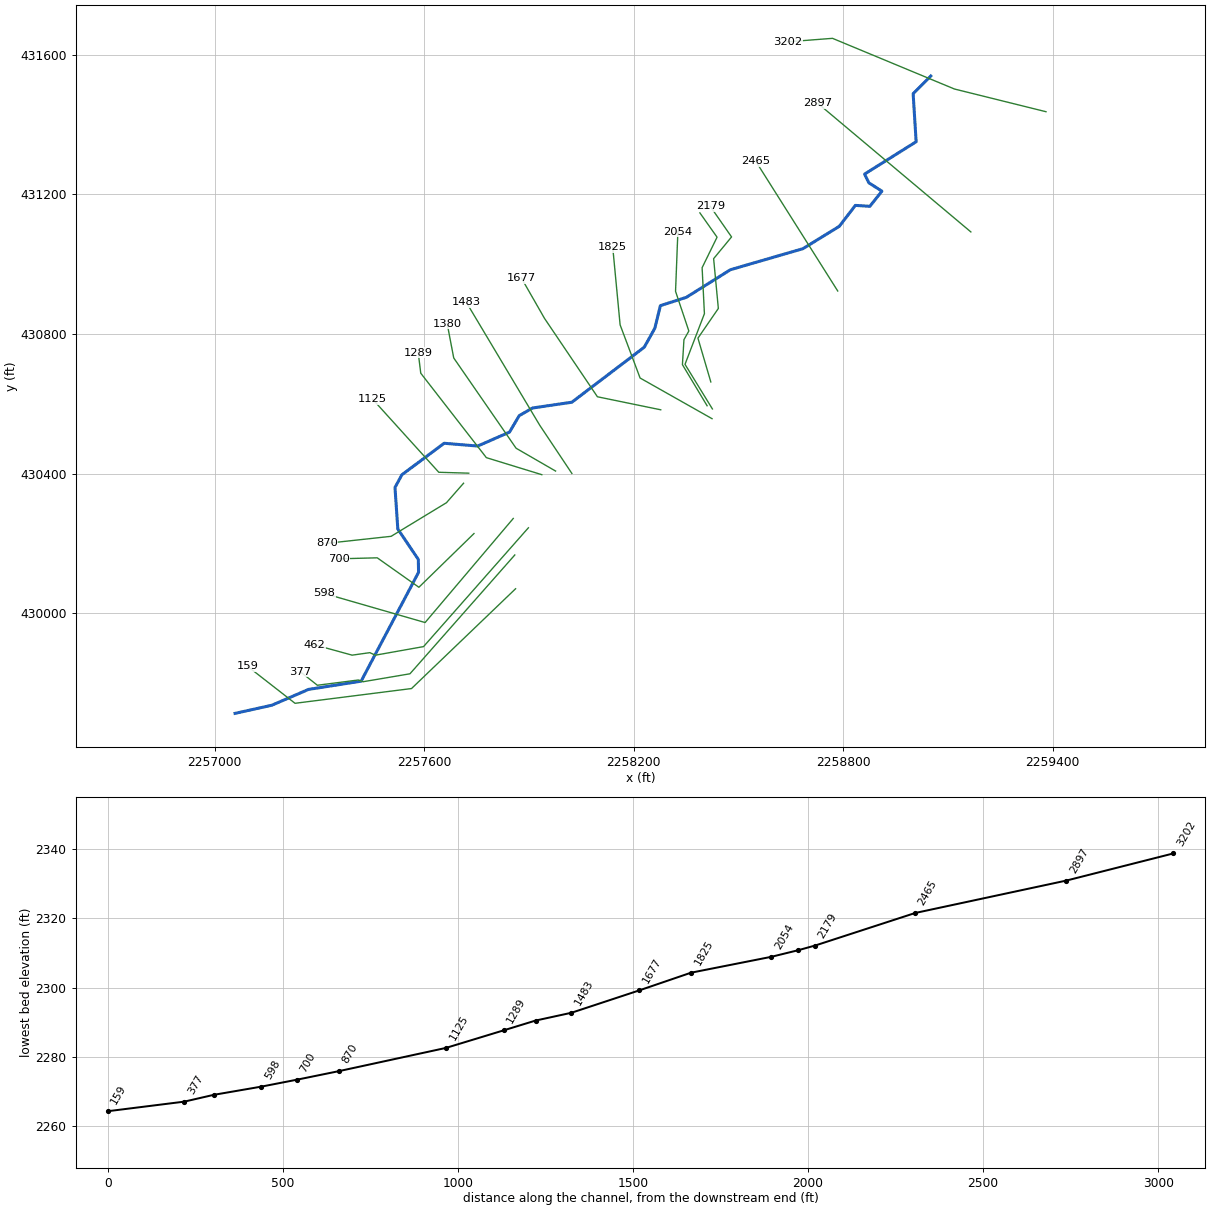
--- KNAPPCKT2.prj (project) ---

Proj Title=KNAPPCKT2
Current Plan=p01
Default Exp/Contr=0,0
English Units
Geom File=g01
Flow File=f01
Plan File=p01
Background Map Layer=Inundation Boundary (01pct Value_0)
BEGIN DESCRIPTION:
----------MODEL BY WOOD PLC 2021----------
Stream Name: Knapp Creek Tributary 2
Flood Zone: Enhanced Approximate
Pocahontas County, WV
HEC-RAS Version: RAS 6.1
Vertical Datum: NAVD88
Projection: NAD 1983 StatePlane West Virginia S FIPS 4702 (US Feet)
Terrain: 1-meter LIDAR (FEMA Region III 3DEP collected 2016-2018)
Land Use: 2019 NLCD
Hydrologic Method:
WV SIR2010-5033 regression equations
Model Notes:
Normal depth tie in to Knapp Creek
END DESCRIPTION:
DSS Export Rating Curves= 0
DSS Export Rating Curve Sorted= 0
DSS Export Volume Flow Curves= 0
DXF OffsetX= 0
DXF OffsetY= 0
DXF ScaleX= 0
DXF ScaleY= 0

--- KNAPPCKT2.p01 (plan) ---

Plan Title=Floodplain
Program Version=6.10
Short Identifier=Floodplain
Geom File=g01
Flow File=f01
Subcritical Flow
K Sum by GR= 0
Std Step Tol= 0.01
Critical Tol= 0.01
Num of Std Step Trials= 20
Max Error Tol= 0.3
Flow Tol Ratio= 0.001
Split Flow NTrial= 30
Split Flow Tol= 0.02
Split Flow Ratio= 0.02
Log Output Level= 0
Friction Slope Method= 1
Unsteady Friction Slope Method= 2
Unsteady Bridges Friction Slope Method= 1
Parabolic Critical Depth
Global Vel Dist= 0 , 0 , 0
Global Log Level= 0
CheckData=True
Encroach Param=-1 ,0,0, 0
Mapping Interval=1HOUR
Computation Time Step Use Courant=        0
Computation Time Step Use Time Series=    0
Computation Time Step Count To Double=0
Computation Time Step Max Doubling=0
Computation Time Step Max Halving=0
Computation Time Step Residence Courant=0
Run HTab= 0
Run UNet= 0
Run Sediment= 0
Run PostProcess= 0
Run WQNet= 0
Run RASMapper=-1
UNET Theta= 0
UNET Theta Warmup= 0
UNET ZTol= 0
UNET ZSATol= 0
UNET MxIter= 0
UNET Max Iter WO Improvement= 0
UNET MaxInSteps= 0
UNET DtIC= 0
UNET DtMin= 0
UNET MaxCRTS= 0
UNET WFStab= 0
UNET SFStab= 0
UNET WFX= 1
UNET SFX= 1
UNET Gravity=32.174
UNET 1D Methodology=Finite Difference
UNET DSS MLevel= 1
UNET Pardiso=0
UNET DZMax Abort= 0
UNET Use Existing IB Tables= 0
UNET Froude Reduction=False
UNET Froude Limit= 0
UNET Froude Power= 0
UNET D1 Cores= 0
UNET WindReference=Eulerian
UNET WindDragFormulation=Hsu (1988)
UNET D2 Coriolis=0
UNET D2 Cores= 0
UNET D2 Theta= 1
UNET D2 Theta Warmup= 1
UNET D2 Z Tol= 0.01
UNET D2 Volume Tol= 0.01
UNET D2 Max Iterations= 20
UNET D2 Equation= 0
UNET D2 RampUpFraction=0.1
UNET D2 TimeSlices= 1
UNET D2 Turbulence Formulation=Non-Conservative (original)
UNET D2 Eddy Viscosity=0.3
UNET D2 Transverse Eddy Viscosity=0.1
UNET D2 Smagorinsky Mixing=0
UNET D2 BCVolumeCheck=0
UNET D2 Cores=0
UNET D2 SolverType=PARDISO (Direct)
UNET D2 Minimum Iterations= 2147483647
UNET D2 Maximum Iterations= 2147483647
UNET D2 Restart Number= 10
UNET D2 Relaxation Coeff=1.3
UNET D2 SOR Precondition Iterations= 10
UNET D2 ILUT Maximum Fill= 8
UNET D2 ILUT Tolerance=1E-08
UNET D1D2 MaxIter= 0
UNET D1D2 ZTol=0.01
UNET D1D2 QTol=0.1
UNET D1D2 MinQTol=1
Write IC File= 0
Write IC File at Fixed DateTime=0
Write IC File at Sim End=0
Echo Input=False
Echo Parameters=False
Echo Output=False
Write Detailed= 0
HDF Write Warmup=0
HDF Write Time Slices=0
HDF Flush=0
HDF Compression= 1
HDF Chunk Size= 1
HDF Spatial Parts= 1
HDF Use Max Rows=0
HDF Fixed Rows= 1
Calibration Method= 0
Calibration Iterations= 20
Calibration Max Change=0.05
Calibration Tolerance=0.2
Calibration Maximum=1.5
Calibration Minimum=0.5
Calibration Optimization Method= 1
WQ AD Non Conservative
WQ ULTIMATE=-1
WQ Max Comp Step=1HOUR
WQ Output Interval=15MIN
WQ Output Selected Increments= 0
WQ Output face flow=0
WQ Output face velocity=0
WQ Output face area=0
WQ Output face dispersion=0
WQ Output cell volume=0
WQ Output cell surface area=0
WQ Output cell continuity=0
WQ Output cumulative cell continuity=0
WQ Output face conc=0
WQ Output face dconc_dx=0
WQ Output face courant=0
WQ Output face peclet=0
WQ Output face adv mass=0
WQ Output face disp mass=0
WQ Output cell mass=0
WQ Output cell source sink temp=0
WQ Output nsm pathways=0
WQ Output nsm derived pathways=0
WQ Create Restart=0
WQ Fixed Restart=0
WQ System Summary=0
WQ Write To DSS=0
Sorting and Armoring Iterations= 10
XS Update Threshold= 0.02
Bed Roughness Predictor= 0
Hydraulics Update Threshold= 0.02
Energy Slope Method= 1
Volume Change Method= 1
Sediment Retention Method= 0
Sediment TS Multiplier= 1
Warm Up Method= 0
XS Weighting Method= 0
Number of US Weighted Cross Sections= 1
Number of DS Weighted Cross Sections= 1
Upstream XS Weight=0
Main XS Weight=1
Downstream XS Weight=0
Number of DS XS's Weighted with US Boundary= 1
Upstream Boundary Weight= 1
Weight of XSs Associated with US Boundary= 0
Number of US XS's Weighted with DS Boundary= 1
Downstream Boundary Weight= 0.5
Weight of XSs Associated with DS Boundary= 0.5
Percentile Method= 0
Sediment Output Level= 3
Mass or Volume Output= 0
Output Increment Type= 1
Profile and TS Output Increment= 1
Transport Output Increment 1
XS Output Flag= 0
XS Output Increment= 10
Read HDF5 Sediment Hotstart= 0
Sediment Hotstart Type= 0
Write Gradation File= 0
Read Gradation Hotstart= 0
Write HDF5 File= 1
Write Binary Output= 1
Write DSS Sediment File= 0
DSS Sediment Output Type= 1
SV Curve= 0
Specific Gage Flag= 0
Subcell Erosion Methods= 0
Subcell Deposition Methods= 0
Advection Scheme= 1
Matrix Solver= 0
Implicit Weighting Factor= 1
Maximum Outer Loop Convergence Iterations= 5
Convergence Maximum Absolute= 0.001
Convergence RMSE= 0.0001
Grain Fractions Max Abs Error= 0.001
Max Subgrid Regions= 1
Max Subgrid Length Scale= 3.402823E+38
Initial Layer Thickness= 3.402823E+38
Min Layer Thickness= 3.402823E+38
Max Layer Thickness= 3.402823E+38
Number of Layers= 5

--- KNAPPCKT2.f01 (steady flow) ---

Flow Title=Flow
Program Version=6.10
Number of Profiles= 6
Profile Names=01pct,10pct,04pct,02pct,0_2pct,01plus
River Rch & RM=KNAPPCKT2,Main,3202
     578     306     406     489     807     855
Boundary for River Rch & Prof#=KNAPPCKT2,Main            , 1
Up Type= 0
Dn Type= 3
Dn Slope=0.01236
Boundary for River Rch & Prof#=KNAPPCKT2,Main            , 2
Up Type= 0
Dn Type= 3
Dn Slope=0.01236
Boundary for River Rch & Prof#=KNAPPCKT2,Main            , 3
Up Type= 0
Dn Type= 3
Dn Slope=0.01236
Boundary for River Rch & Prof#=KNAPPCKT2,Main            , 4
Up Type= 0
Dn Type= 3
Dn Slope=0.01236
Boundary for River Rch & Prof#=KNAPPCKT2,Main            , 5
Up Type= 0
Dn Type= 3
Dn Slope=0.01236
Boundary for River Rch & Prof#=KNAPPCKT2,Main            , 6
Up Type= 0
Dn Type= 3
Dn Slope=0.01236
DSS Import GetInterval= 0
DSS Import GetPeak= 0
DSS Import FillOption= 0

--- KNAPPCKT2.g01 (geometry) ---

Geom Title=Geometry
Program Version=6.10

River Reach=KNAPPCKT2       ,Main
Reach XY= 30
     2259051.313      431539.299      2259000.66      431488.545
2259009.25076822431350.9982026522258861.52297416431258.329061493
2258873.74794512431233.4134219542258911.15330917431209.474200463
2258876.64471686431166.047657326     2258835.224      431168.715
 2258789.0161566431108.662582466     2258685.069      431044.741
     2258477.405      430984.498     2258350.976      430905.337
      2258276.82      430881.633     2258260.985      430817.094
     2258230.616      430762.5362258023.23559681430604.992229471
     2257910.562      430588.432     2257872.535       430566.55
     2257844.698      430519.432     2257753.645      430479.497
     2257657.477      430487.469      2257536.57      430397.247
     2257516.697      430360.921 2257524.8458108430241.814854585
     2257583.516      430154.878     2257584.293      430118.048
     2257419.753      429806.103     2257269.019        429782.5
     2257164.077      429737.214     2257058.754        429713.9

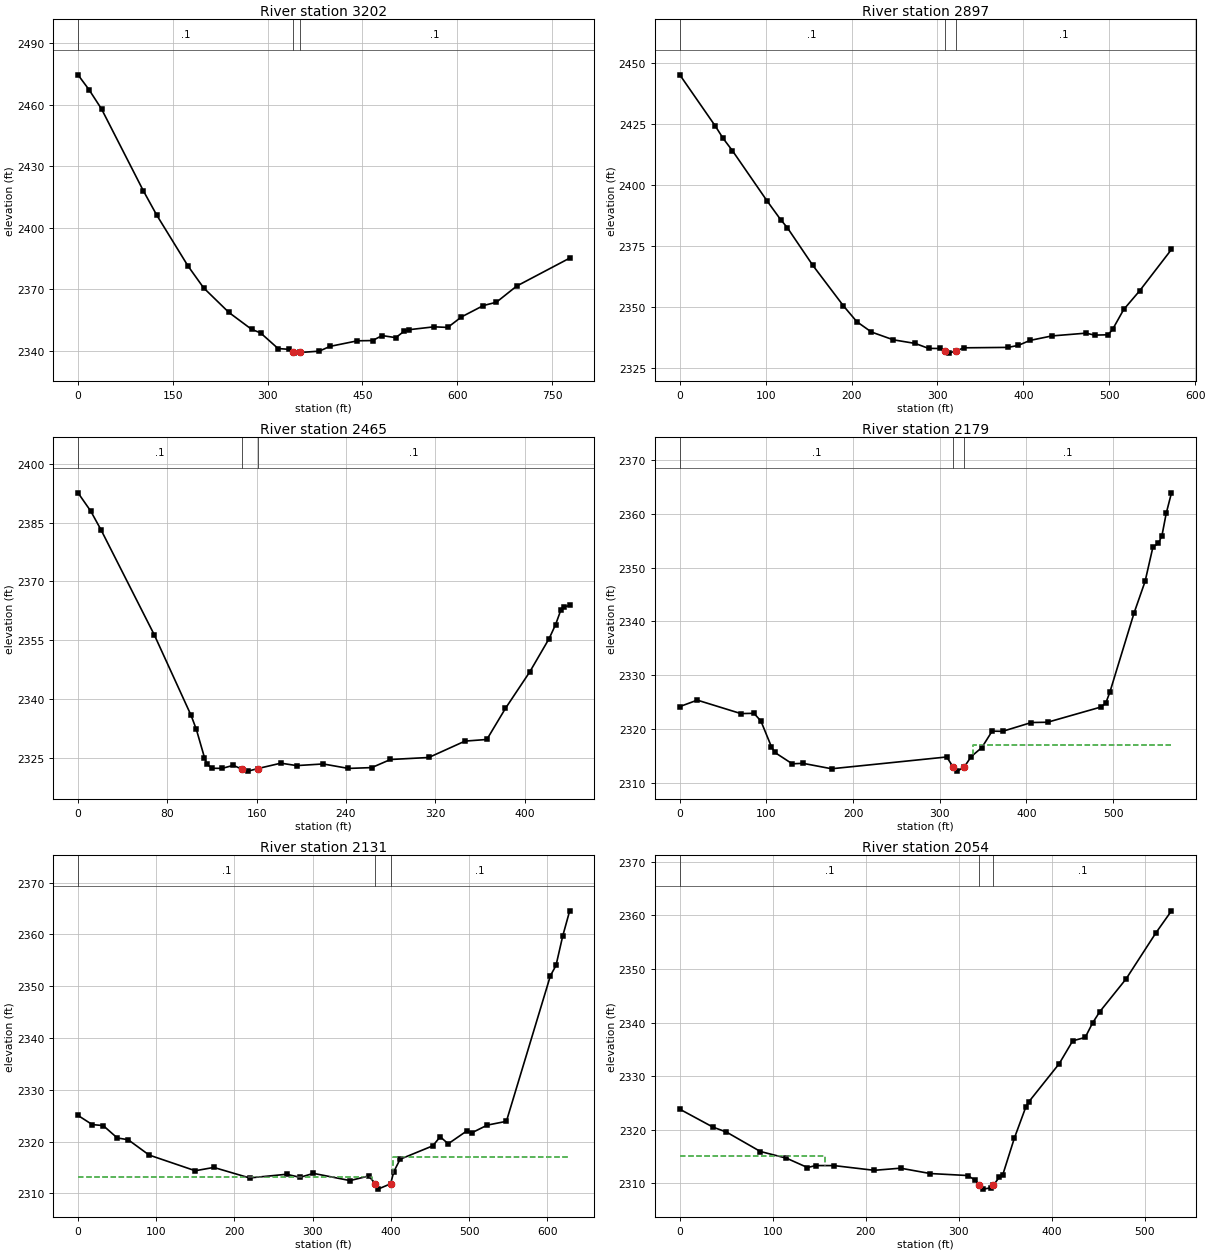
Type RM Length L Ch R = 1 ,3202    ,305.5,305.5,305.5
XS GIS Cut Line= 4
2259381.16492035431436.9758540072259118.95087936431502.028955779
2258769.66576369431647.147413577 2258640.5603771431637.139244074
#Sta/Elev= 30
       0 2474.62    17.5 2467.34    37.3 2457.92   103.3 2418.07   124.7 2406.08
   174.1 2381.29   198.8 2370.63   238.7 2358.66   274.7  2350.4   288.8 2348.68
   316.5 2341.05   333.8 2340.65   340.9 2339.18   342.5  2338.8   351.2 2339.12
   381.5 2339.75   398.8  2342.1   442.1 2344.81     466 2344.94   481.1 2347.36
   502.7 2346.36   515.7 2349.41   524.4 2350.26   563.4 2351.64     585 2351.34
   606.7 2356.47   641.3 2362.02   661.9 2363.63     694 2371.52   777.9 2385.17
#Mann= 3 ,-1,0
       0      .1       0   340.9    .045       0   351.2      .1       0
Bank Sta=340.9,351.2
XS Rating Curve= 0 ,0
Exp/Cntr(USF)=0,0
Exp/Cntr=0.3,0.1

Type RM Length L Ch R = 1 ,2897    ,358.5,432.2,339.8
XS GIS Cut Line= 2
2259165.98927602431092.6948230922258727.63145178431460.995460815
#Sta/Elev= 30
       0 2445.09    41.4 2424.06    50.5    2419    61.3 2413.97   101.6 2393.39
   117.3 2385.76   125.1 2382.46   154.9 2366.94   190.4 2350.41   206.1 2343.86
   223.1 2339.62   248.6 2336.42     274 2334.94   289.7  2332.9   302.6 2332.86
   308.3 2331.79   313.9 2330.96   321.1 2331.85     331 2333.14   382.1 2333.31
   394.2 2334.14   407.6 2336.16   433.2 2338.01   472.9 2339.15     483 2338.35
   498.7 2338.48   503.9 2340.68   516.9 2348.87   535.3 2356.46   572.5 2373.49
#Mann= 3 ,-1,0
       0      .1       0   308.3    .045       0   321.1      .1       0
Bank Sta=308.3,321.1
XS Rating Curve= 0 ,0
Exp/Cntr(USF)=0,0
Exp/Cntr=0.3,0.1

Type RM Length L Ch R = 1 ,2465    ,285,285.3,273.4
BEGIN DESCRIPTION:
structure xs 4
END DESCRIPTION:
XS GIS Cut Line= 2
2258784.67801795430923.5567584852258549.48603462 431295.86066401
#Sta/Elev= 30
       0 2392.61    11.4 2387.95    20.8 2383.06    68.2 2356.44   101.3  2335.8
     106 2332.23   113.3 2325.02   115.5 2323.35   120.2 2322.31   129.1 2322.28
   139.1 2323.06   146.5 2322.12   152.3 2321.58     161 2322.23   181.7 2323.61
   195.9 2322.99   219.6 2323.41   242.2 2322.27   263.1 2322.48   279.9 2324.55
   314.2 2325.06   346.6 2329.24   366.2 2329.66   382.9 2337.61   404.6 2346.89
     422 2355.42   427.8    2359   432.5 2362.72   435.3 2363.51   440.4 2363.86
#Mann= 3 ,-1,0
       0      .1       0   146.5    .045       0     161      .1       0
Bank Sta=146.5,161
XS Rating Curve= 0 ,0
Exp/Cntr(USF)=0,0
Exp/Cntr=0.5,0.3

Type RM Length L Ch R = 1 ,2179    ,47.1,48.2,45.8
BEGIN DESCRIPTION:
structure xs 3; 10.1 ft between structure and xs
END DESCRIPTION:
XS GIS Cut Line= 6
2258421.23083994430663.0756753922258384.33067863430788.493747795
2258442.79442739430873.5443504852258429.24989985431016.137561664
2258480.62690427431078.3918648422258419.48340709431166.244574078
#Sta/Elev= 30
       0 2324.18    20.2 2325.38    70.5 2322.88    85.6 2322.93    93.6  2321.5
   105.7 2316.74   109.7 2315.66   129.8 2313.55   142.1 2313.64   175.2 2312.63
   308.1 2314.82   315.4 2312.97   320.3 2312.19   328.3 2312.96   336.4  2314.9
   348.6 2316.57   360.5 2319.62   372.5 2319.58   405.8 2321.22   424.4 2321.27
   485.9 2324.09   491.6 2324.81   496.3 2326.82   524.3 2341.56     537 2347.42
   546.1 2353.83   552.3 2354.48   556.5 2355.94   561.4 2360.06   567.5 2363.89
#Mann= 3 ,-1,0
       0      .1       0   315.4    .045       0   328.3      .1       0
#XS Ineff= 2 , 0
             305  2313.1     338            2317
Permanent Ineff=
       F       F
Bank Sta=315.4,328.3
XS Rating Curve= 0 ,0
Exp/Cntr(USF)=0,0
Exp/Cntr=0.5,0.3

Type RM Length L Ch R = 1 ,2131    ,73.1,76.8,81.6
BEGIN DESCRIPTION:
structure xs 2; 13.2 ft between structure and xs
END DESCRIPTION:
XS GIS Cut Line= 6
2258425.73632011430585.7613123682258347.29450082 430713.51286797
2258402.89004264430858.5197966322258396.30018121430990.317350312
2258439.10505871431077.640178791 2258389.9173687431147.283445864
#Sta/Elev= 30
       0 2325.07    18.2  2323.3    32.2 2323.11    50.2 2320.72    64.1 2320.38
    90.9 2317.42   149.9 2314.39   173.6 2315.03   219.3    2313   266.6 2313.71
   283.8 2313.12     301 2313.88   347.7 2312.49   371.4 2313.37   380.1 2311.92
   383.5 2310.84   399.6 2311.87   403.6 2314.18   411.7 2316.61   453.5  2319.2
     463 2320.95   473.2 2319.59   497.7 2322.15   503.2  2321.7   523.2  2323.2
   547.6 2323.93   603.8 2352.02     611 2354.03   619.6 2359.71   628.5 2364.57
#Mann= 3 ,-1,0
       0      .1       0   380.1    .045       0   399.6      .1       0
#XS Ineff= 2 , 0
             376  2313.1     403            2317
Permanent Ineff=
       F       F
Bank Sta=380.1,399.6
XS Rating Curve= 0 ,0
Exp/Cntr(USF)=0,0
Exp/Cntr=0.5,0.3

Type RM Length L Ch R = 1 ,2054    ,229.1,229.8,231.1
BEGIN DESCRIPTION:
structure xs 1
END DESCRIPTION:
XS GIS Cut Line= 6
 2258410.6030394430594.8718697372258339.89308339 430712.61422551
2258344.28142002430784.2084062062258358.29048809430808.846803941
2258320.21835971430922.6075004472258326.89047271431093.858400838
#Sta/Elev= 30
       0 2323.85    35.8 2320.49    50.1 2319.59    86.7 2315.95   114.7 2314.71
   137.3 2312.96   146.2 2313.33     166 2313.32   209.1 2312.44   237.4 2312.84
   269.3 2311.84   309.5 2311.47   317.9 2310.59   322.1 2309.66   326.3 2308.93
   334.8 2309.18   337.3 2309.66   343.6 2311.15   347.4 2311.63   359.8 2318.44
     372 2324.19   375.2 2325.19     408 2332.33   422.6 2336.61     436 2337.24
     444 2339.96   451.7 2342.05     480 2348.17   512.1 2356.77   528.8 2360.87
#Mann= 3 ,-1,0
       0      .1       0   322.1    .045       0   337.3      .1       0
#XS Ineff= 2 , 0
          156.11 2315.17
Permanent Ineff=
       F       F
Bank Sta=322.1,337.3
XS Rating Curve= 0 ,0
Exp/Cntr(USF)=0,0
Exp/Cntr=0.3,0.1

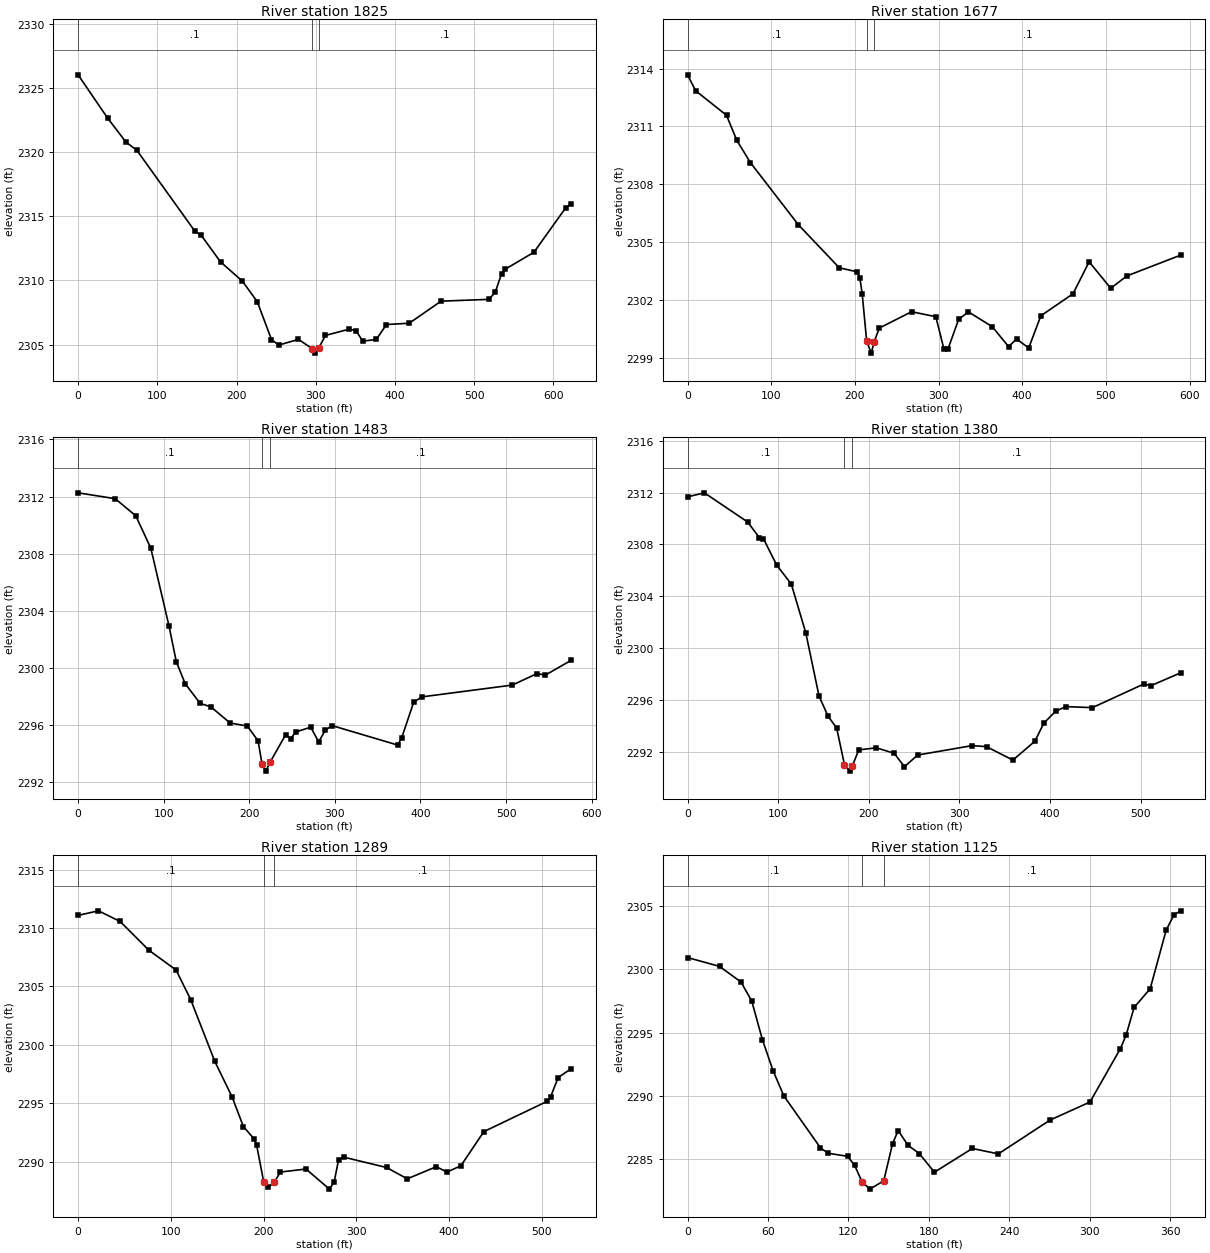
Type RM Length L Ch R = 1 ,1825    ,144.9,147.5,149.2
XS GIS Cut Line= 4
2258424.74813008430557.8653229912258218.68109118430674.325270725
2258161.45369472430826.6320283242258140.34316937431048.811044997
#Sta/Elev= 30
       0 2326.02    37.4 2322.64    60.4 2320.78    74.2 2320.14   147.7 2313.81
   155.5 2313.51   179.8 2311.44   207.4 2309.94   226.2 2308.34   244.1 2305.39
   253.3 2304.96   278.2  2305.4  295.462304.686   299.6 2304.33   303.8 2304.73
   312.3 2305.71   342.3  2306.2   350.8 2306.08   359.4 2305.26   376.5  2305.4
   389.3 2306.56     418 2306.66   458.2 2308.38   518.5 2308.52   526.5 2309.07
   534.6 2310.52   538.6 2310.85   575.4 2312.19   615.7 2315.67   622.6 2315.95
#Mann= 3 ,-1,0
       0      .1       0  295.46    .045       0   303.8      .1       0
Bank Sta=295.46,303.8
XS Rating Curve= 0 ,0
Exp/Cntr(USF)=0,0
Exp/Cntr=0.3,0.1

Type RM Length L Ch R = 1 ,1677    ,194.1,193.8,193.3
XS GIS Cut Line= 4
2258277.82176749430583.3195740932258096.48126735430620.627202009
2257945.05647482430844.9340208532257878.54278091430960.979188962
#Sta/Elev= 30
       0 2313.68     9.8 2312.85    46.6 2311.58    58.9 2310.28    75.2 2309.12
   132.4  2305.9   181.4 2303.66     203 2303.45   205.9 2303.15   208.8  2302.3
   214.12299.857   219.6 2299.23   222.92299.798   229.2 2300.53   267.8 2301.38
   296.8 2301.12   306.5 2299.43   311.3 2299.44   324.1 2300.99   335.8 2301.37
   364.3  2300.6   383.7 2299.57   393.3 2299.96   407.8  2299.5   422.3 2301.17
   460.7 2302.31     480 2303.97   505.8  2302.6   525.2 2303.24   589.5 2304.32
#Mann= 3 ,-1,0
       0      .1       0   214.1    .045       0   222.9      .1       0
Bank Sta=214.1,222.9
XS Rating Curve= 0 ,0
Exp/Cntr(USF)=0,0
Exp/Cntr=0.3,0.1

Type RM Length L Ch R = 1 ,1483    ,101.8,102.6,102.8
XS GIS Cut Line= 3
2258023.30933111430401.0706674392257930.94312477430539.578791061
2257720.84020834430891.470973103
#Sta/Elev= 30
       0 2312.26    43.4 2311.85    67.4 2310.65      85 2308.38   106.2 2302.94
   114.8 2300.42   125.1 2298.89   142.6 2297.51   155.2 2297.26   177.7 2296.13
   197.8 2295.92   210.3 2294.88   214.9 2293.27   219.3 2292.76   224.2 2293.37
   242.6 2295.32   248.4 2295.04   254.3  2295.5   271.8 2295.84   281.1 2294.81
   288.9 2295.63   296.7 2295.95   373.3 2294.59     378 2295.07     392 2297.57
   401.3 2297.96   507.4 2298.79   536.4  2299.6   545.7 2299.48   576.3 2300.53
#Mann= 3 ,-1,0
       0      .1       0   214.9    .045       0   224.2      .1       0
Bank Sta=214.9,224.2
XS Rating Curve= 0 ,0
Exp/Cntr(USF)=0,0
Exp/Cntr=0.3,0.1

Type RM Length L Ch R = 1 ,1380    ,90.1,91.2,92.1
XS GIS Cut Line= 4
 2257976.6404539 430407.894466822257863.49789529430473.288789686
2257684.96101381430731.7520657782257666.27692156430829.324547515
#Sta/Elev= 30
       0 2311.67    18.6 2311.98    66.5 2309.72    79.1 2308.53    83.7 2308.45
    98.5 2306.39   114.5 2304.94   130.5 2301.17   145.1  2296.3   154.9 2294.76
   164.6 2293.82   173.2 2290.98   178.8  2290.5   181.9  2290.9   188.9 2292.14
   208.3  2292.3   227.9 2291.88   239.4 2290.84   253.8 2291.74   314.1 2292.47
   329.9 2292.39     359 2291.35   383.3 2292.81   393.1  2294.2   406.1 2295.12
   417.4 2295.48   446.7  2295.4   503.3 2297.22   511.4  2297.1   544.2 2298.09
#Mann= 3 ,-1,0
       0      .1       0   173.2    .045       0   181.9      .1       0
Bank Sta=173.2,181.9
XS Rating Curve= 0 ,0
Exp/Cntr(USF)=0,0
Exp/Cntr=0.3,0.1

Type RM Length L Ch R = 1 ,1289    ,162.3,164.7,165.8
XS GIS Cut Line= 4
2257937.19625915430397.5144155712257778.38147505 430446.30065644
2257590.50254745430688.1558505332257583.23651157430747.322142651
#Sta/Elev= 30
       0 2311.08      22 2311.47    45.4 2310.56    76.4  2308.1   105.7 2306.41
   121.5 2303.87   147.5 2298.59   166.1 2295.56   178.3 2293.02     190 2291.95
   192.6 2291.42   200.2  2288.3   205.2 2287.82   211.7 2288.28   218.2 2289.13
   245.8 2289.39   271.1 2287.67   276.2 2288.29   280.9 2290.15   286.3 2290.41
   332.7 2289.52   355.1 2288.55   386.4 2289.59   397.9 2289.13   412.9 2289.67
   437.7 2292.59   505.7 2295.17   509.7 2295.57   517.8 2297.21     532 2297.98
#Mann= 3 ,-1,0
       0      .1       0   200.2    .045       0   211.7      .1       0
Bank Sta=200.2,211.7
XS Rating Curve= 0 ,0
Exp/Cntr(USF)=0,0
Exp/Cntr=0.3,0.1

Type RM Length L Ch R = 1 ,1125    ,293.5,304.8,315.2
XS GIS Cut Line= 3
2257728.05580833430401.8203616112257642.16518318430404.370227128
2257452.84366942430613.466264677
#Sta/Elev= 30
       0 2300.94    23.9 2300.24    39.9    2299    47.9  2297.5    55.9 2294.43
    63.9 2291.96    71.9 2289.98    99.2 2285.87   104.9 2285.44   119.4  2285.2
   124.7 2284.48   130.2 2283.18   136.1  2282.6   146.4 2283.26     153 2286.21
   157.2 2287.24   164.4 2286.08   172.9 2285.42   184.2 2283.94   212.5 2285.82
   231.9 2285.39   270.5 2288.07   300.3  2289.5     323 2293.73   327.3 2294.82
   333.2 2296.99   345.2 2298.47   357.1 2303.11     363 2304.33     368 2304.64
#Mann= 3 ,-1,0
       0      .1       0   130.2    .045       0   146.4      .1       0
Bank Sta=130.2,146.4
XS Rating Curve= 0 ,0
Exp/Cntr(USF)=0,0
Exp/Cntr=0.3,0.1

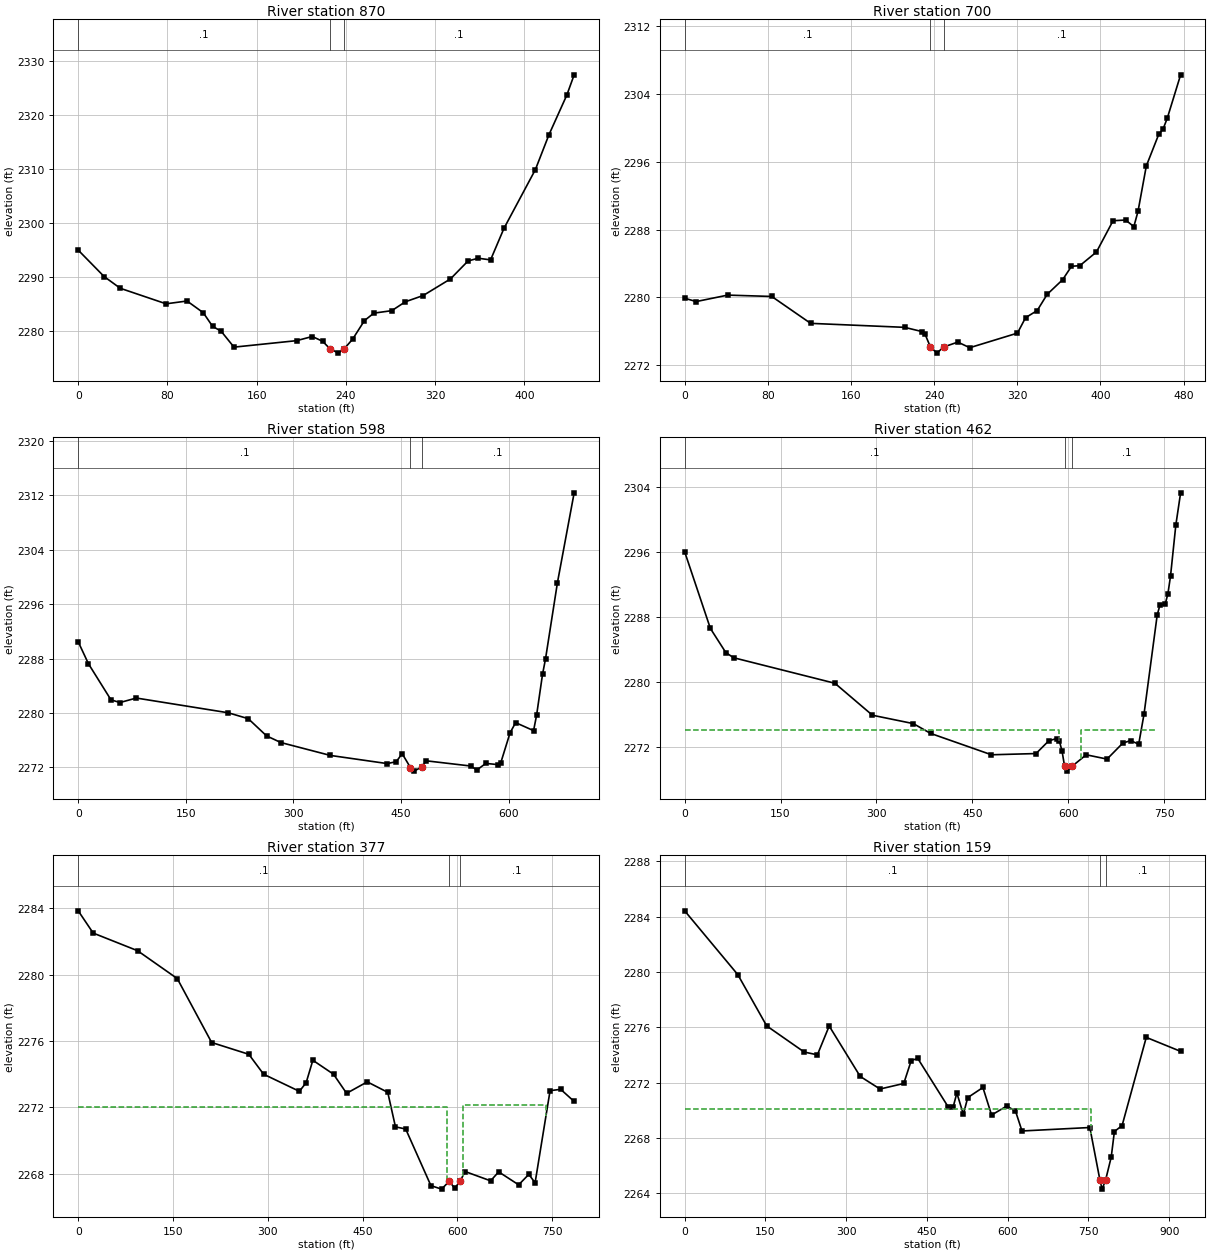
Type RM Length L Ch R = 1 ,870     ,127.9,120.2,111.3
XS GIS Cut Line= 4
2257713.08476115430373.0020510222257664.01221625430317.138016347
2257505.65702827430220.9641849042257321.62544704430200.907277371
#Sta/Elev= 30
       0    2295    23.2 2290.11    37.7 2287.93    78.8 2285.05    97.6 2285.57
   112.1 2283.41   120.5 2280.88   128.2 2279.96   139.7 2277.02   195.8 2278.22
   209.9 2278.99   219.2  2278.1   225.6 2276.75   233.3 2275.91  238.61 2276.74
     246 2278.47   256.7 2281.94   265.1 2283.32   281.2 2283.78   293.4 2285.43
   309.4 2286.59   333.8 2289.66   349.6 2292.99   358.7  2293.5   369.8 2293.19
   381.8 2299.03     410 2309.93   422.1 2316.36   438.2 2323.75444.7501 2327.49
#Mann= 3 ,-1,0
       0      .1       0   225.6    .045       0  238.61      .1       0
Bank Sta=225.6,238.61
XS Rating Curve= 0 ,0
Exp/Cntr(USF)=0,0
Exp/Cntr=0.3,0.1

Type RM Length L Ch R = 1 ,700     ,97,101.9,105.5
XS GIS Cut Line= 4
2257742.96182864430228.9332035472257585.18310793430075.045969742
2257465.87843298430159.4078057562257355.22610968430156.495902511
#Sta/Elev= 30
       0  2279.9    11.1 2279.51    41.4 2280.27    83.8 2280.11   121.2 2276.94
   211.6 2276.47   228.4 2275.97   231.3 2275.66236.37332274.173   242.7 2273.43
   249.1 2274.15   262.8 2274.73   274.3 2274.07   320.2 2275.79     328 2277.61
   339.2 2278.45   348.8 2280.36   363.7 2282.09   372.2 2283.67   380.2 2283.74
   396.2 2285.35   412.2 2289.04   424.2 2289.12   432.2 2288.35   436.2 2290.14
   444.2  2295.5   456.1 2299.21   460.3 2299.85   464.3  2301.1   477.2 2306.24
#Mann= 3 ,-1,0
       0      .1       0236.3733    .045       0   249.1      .1       0
Bank Sta=236.3733,249.1
XS Rating Curve= 0 ,0
Exp/Cntr(USF)=0,0
Exp/Cntr=0.3,0.1

Type RM Length L Ch R = 1 ,598     ,134.7,135.9,133.8
BEGIN DESCRIPTION:
structure xs 4
END DESCRIPTION:
XS GIS Cut Line= 3
2257855.39448722430272.0764827292257602.96621197429974.055435295
 2257313.8413152430057.456847823
#Sta/Elev= 30
       0 2290.46    14.3 2287.22    45.7 2281.91    58.3 2281.52      81 2282.18
   209.2 2280.01   237.1 2279.14   262.6 2276.61   282.5 2275.63   351.6 2273.73
   430.9 2272.53   443.4 2272.81   451.7 2273.99   463.2 2271.95   468.4 2271.42
   479.3 2272.06   485.1 2272.94   547.5 2272.17   555.8 2271.58   568.3 2272.56
     585 2272.38   589.1 2272.62   602.1 2277.05   609.9 2278.56   634.9 2277.38
   639.1 2279.63   647.4 2285.67   651.6 2287.96   668.2 2299.17   691.5 2312.39
#Mann= 3 ,-1,0
       0      .1       0   463.2    .045       0   479.3      .1       0
Bank Sta=463.2,479.3
XS Rating Curve= 0 ,0
Exp/Cntr(USF)=0,0
Exp/Cntr=0.5,0.3

Type RM Length L Ch R = 1 ,462     ,82.3,84.4,201.4
BEGIN DESCRIPTION:
structure xs 3; 8.7 ft between structure and xs
END DESCRIPTION:
XS GIS Cut Line= 6
2257898.76322173 430245.388030722257598.51813663429905.110267605
2257460.20623203429880.516960618 2257444.8408905429887.811894388
2257393.90667123429880.6458532642257284.92882553429910.670361774
#Sta/Elev= 30
       0 2296.01    40.2 2286.59    64.3 2283.63    76.5 2282.99     235 2279.85
   293.7 2275.92   357.7 2274.89   384.6 2273.69   479.9 2271.06   549.6 2271.21
   569.6 2272.78   582.1 2273.06   586.2 2272.72   590.3 2271.52   594.3 2269.64
   597.8 2269.05  605.832269.634   628.1 2271.06   660.7 2270.53   685.3 2272.49
   697.7 2272.81   710.2 2272.35   718.5 2276.03   739.2 2288.26   743.4 2289.44
   751.7  2289.6   755.8  2290.8     760 2293.02   768.3  2299.3   775.8 2303.26
#Mann= 3 ,-1,0
       0      .1       0   594.3    .045       0  605.83      .1       0
#XS Ineff= 2 ,-1
       0   585.6 2274.09  619.81  737.79 2274.09
Permanent Ineff=
       F       F
Bank Sta=594.3,605.83
XS Rating Curve= 0 ,0
Exp/Cntr(USF)=0,0
Exp/Cntr=0.5,0.3

Type RM Length L Ch R = 1 ,377     ,218.7,218.7,218.7
BEGIN DESCRIPTION:
structure xs 2; 9.7 ft between structure
END DESCRIPTION:
XS GIS Cut Line= 6
2257859.84256255 430167.546712362257559.59747745429827.268949246
2257425.32213585429804.5002988722257411.75134112429809.540879771
2257294.43202498 429794.427501122257246.00816635429832.829043414
#Sta/Elev= 30
       0 2283.84    23.7  2282.5    93.8 2281.44   156.7 2279.76   211.1 2275.91
   269.9  2275.2   293.3    2274   349.9 2272.97   360.6 2273.49   371.2 2274.84
   403.9    2274   424.6 2272.85   457.3 2273.54   489.7 2272.91   501.9 2270.83
   518.1  2270.7     558 2267.29   574.9 2267.08   587.1 2267.56   595.5 2267.13
   603.9 2267.54   612.1 2268.14   652.4 2267.58   665.2 2268.12   696.8 2267.34
   712.9 2267.97   722.8 2267.46   746.5 2273.01   763.3 2273.09   784.6 2272.36
#Mann= 3 ,-1,0
       0      .1       0   587.1    .045       0   603.9      .1       0
#XS Ineff= 2 ,-1
       0     584    2272  608.11  740.092272.142
Permanent Ineff=
       F       F
Bank Sta=587.1,603.9
XS Rating Curve= 0 ,0
Exp/Cntr(USF)=0,0
Exp/Cntr=0.5,0.3

Type RM Length L Ch R = 1 ,159     ,,,
BEGIN DESCRIPTION:
structure xs 1
END DESCRIPTION:
XS GIS Cut Line= 4
2257862.06660022430070.8010738282257564.04555279429785.012233565
2257230.43990268429742.7555178842257094.77360496429848.397307086
#Sta/Elev= 30
       0 2284.41    98.7  2279.8   152.3  2276.1     222 2274.21   246.5 2274.01
   268.4 2276.09     326 2272.45   362.8 2271.54   406.9 2271.94   420.8  2273.6
   432.9 2273.75   489.4 2270.25   498.5 2270.22   505.5 2271.25   517.6 2269.72
   525.7 2270.92   553.9 2271.65     570 2269.66   598.2 2270.31   614.4 2269.95
   626.5 2268.51   752.5 2268.76   771.2 2264.97   775.3 2264.31  781.662264.952
   792.2 2266.62   798.1 2268.47   812.4  2268.9   857.3 2275.27   921.1 2274.26
#Mann= 3 ,-1,0
       0      .1       0   771.2    .045       0  781.66      .1       0
#XS Ineff= 2 , 0
          754.93 2270.13
Permanent Ineff=
       F       F
Bank Sta=771.2,781.66
XS Rating Curve= 0 ,0
Exp/Cntr(USF)=0,0
Exp/Cntr=0.3,0.1
LCMann Table=0

Chan Stop Cuts=-1
Use User Specified Reach Order=0
Composite Channel Slope=5